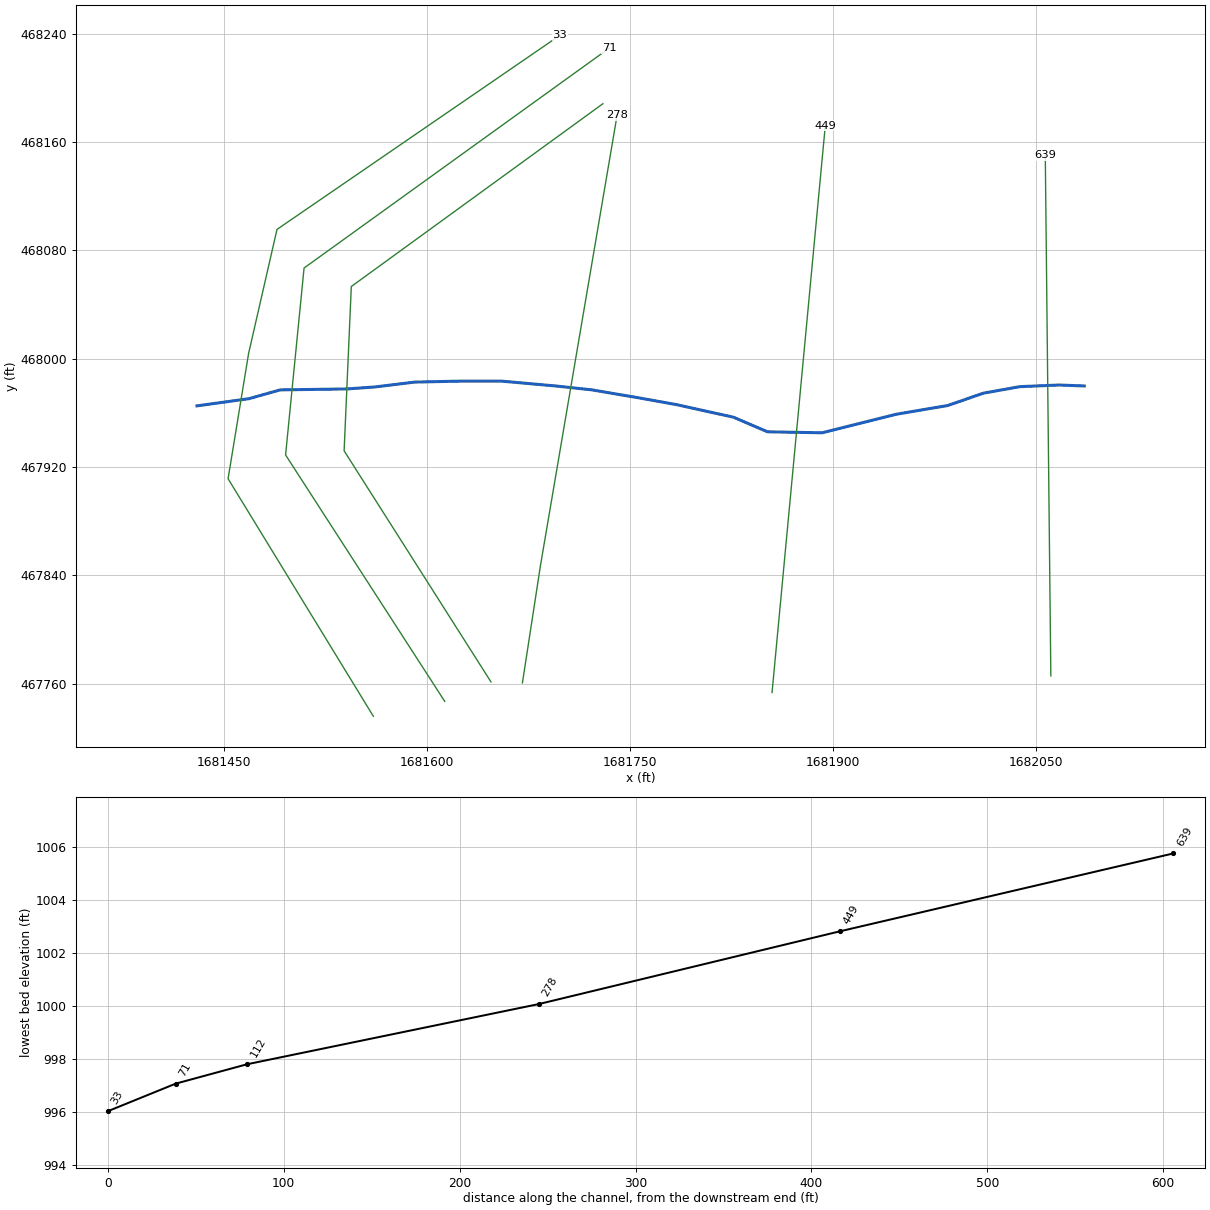
--- HrtRnT1.prj (project) ---

Proj Title=HrtRnT1
Current Plan=p01
Default Exp/Contr=0.3,0.1
English Units
Geom File=g01
Flow File=f01
Plan File=p01
Y Axis Title=Elevation
X Axis Title(PF)=Main Channel Distance
X Axis Title(XS)=Station
BEGIN DESCRIPTION:
---------- MODELED AS PART OF WVEM CTP PROGRAM, 2025----------
Stream Name: Hart Run Tributary 1
Flood Zone: AFH
Marshall County, WV
HEC-RAS Version: RAS 6.6
Vertical Datum: NAVD88
Projection: NAD 1983 StatePlane West Virginia N FIPS 4701 (US Feet)
Terrain: 1-meter West Virginia FEMA R3 South Central (collected 2018-2019)
Land Use: 2024 NLCD
Hydrologic Method:
Duda et al., "Estimation of magnitude and frequency of floods for rural, unregulated streams in and near Virginia and West Virginia." September 8, 2025.
Additional Model Notes:
None
END DESCRIPTION:
DSS Export Rating Curves= 0
DSS Export Rating Curve Sorted= 0
DSS Export Volume Flow Curves= 0
DXF OffsetX= 0
DXF OffsetY= 0
DXF ScaleX= 1
DXF ScaleY= 10

--- HrtRnT1.p01 (plan) ---

Plan Title=Floodplain
Program Version=6.60
Short Identifier=Floodplain
Geom File=g01
Flow File=f01
Subcritical Flow
K Sum by GR= 0
Std Step Tol= 0.01
Critical Tol= 0.01
Num of Std Step Trials= 20
Max Error Tol= 0.3
Flow Tol Ratio= 0.001
Split Flow NTrial= 30
Split Flow Tol= 0.02
Split Flow Ratio= 0.02
Log Output Level= 0
Friction Slope Method= 1
Unsteady Friction Slope Method= 2
Unsteady Bridges Friction Slope Method= 1
Parabolic Critical Depth
Global Vel Dist= 0 , 0 , 0
Global Log Level= 0
CheckData=True
Encroach Param=-1 ,0,0, 0
Flow Ratio Tolerance=0.1
Flow Ratio Min Ratio=0.5
Flow Ratio Max Ratio=4
Flow Ratio Max Iterations= 10
Computation Interval=1MIN
Output Interval=1HOUR
Instantaneous Interval=1HOUR
Mapping Interval=1HOUR
Computation Time Step Use Courant=        0
Computation Time Step Use Time Series=    0
Computation Time Step Count To Double=0
Computation Time Step Max Doubling=0
Computation Time Step Max Halving=0
Computation Time Step Residence Courant=0
Run HTab= 0
Run UNet= 0
Run Sediment= 0
Run PostProcess= 0
Run WQNet= 0
Run RASMapper=-1
UNET Theta= 1
UNET Theta Warmup= 1
UNET ZTol= 0.02
UNET ZSATol= 0.02
UNET MxIter= 20
UNET Max Iter WO Improvement= 0
UNET MaxInSteps= 0
UNET DtIC= 0
UNET DtMin= 0
UNET MaxCRTS= 20
UNET WFStab= 2
UNET SFStab= 1
UNET WFX= 1
UNET SFX= 1
UNET Gravity=32.17405
UNET 1D Methodology=Finite Difference
UNET DSS MLevel= 4
UNET Pardiso=0
UNET DZMax Abort= 100
UNET Use Existing IB Tables=-1
UNET Froude Reduction=False
UNET Froude Limit= 0.8
UNET Froude Power= 4
UNET D1 Cores= 0
UNET WindReference=Eulerian
UNET WindDragFormulation=Hsu (1988)
UNET D2 Coriolis=0
UNET D2 Cores= 0
UNET D2 Theta= 1
UNET D2 Theta Warmup= 1
UNET D2 Z Tol= 0.01
UNET D2 Volume Tol= 0.01
UNET D2 Max Iterations= 20
UNET D2 Advanced Convergence=0
UNET D2 WS Max Tol=0.15
UNET D2 WS RMS Tol=0.002
UNET D2 WS Stall Tol=1
UNET D2 Equation= 0
UNET D2 RampUpFraction=0.1
UNET D2 TimeSlices= 1
UNET D2 Turbulence Formulation=None
UNET D2 Eddy Viscosity=0.3
UNET D2 Transverse Eddy Viscosity=0.1
UNET D2 Smagorinsky Mixing=0.05
UNET D2 BCVolumeCheck=0
UNET D2 Cores=0
UNET D2 SolverType=PARDISO (Direct)
UNET D2 Minimum Iterations= 3
UNET D2 Maximum Iterations= 30
UNET D2 Restart Number= 10
UNET D2 Relaxation Coeff=1.3
UNET D2 SOR Precondition Iterations= 10
UNET D2 ILUT Maximum Fill= 8
UNET D2 ILUT Tolerance=1E-08
UNET D2 Convergence Tolerance=0.00001
PS Theta= 1
PS WS Tol= 0.01
PS Volume Tol= 0.01
PS Max Iterations= 20
PS Equation= 0
PS Advance Time Step=-1
PS Target Courant=0.9
PS Time Slices= 1
PS Iterate With 2D=0
PS Project Initial WSE from DS=-1
PS Ramp Up Initial WSE from US=-1
PS Cores=0
UNET D1D2 MaxIter= 0
UNET D1D2 ZTol=0.01
UNET D1D2 QTol=0.1
UNET D1D2 MinQTol=1
Write IC File= 0
Write IC File at Fixed DateTime=0
Write IC File at Sim End=0
Echo Input=False
Echo Parameters=False
Echo Output=False
Write Detailed= 0
HDF Write Warmup=0
HDF Write Time Slices=0
HDF Flush=0
HDF Compression= 1
HDF Chunk Size= 1
HDF Spatial Parts= 1
HDF Use Max Rows=0
HDF Fixed Rows= 1
Calibration Method= 0
Calibration Iterations= 20
Calibration Max Change=0.05
Calibration Tolerance=0.2
Calibration Maximum=1.5
Calibration Minimum=0.5
Calibration Optimization Method= 1
WQ AD Non Conservative
WQ ULTIMATE=-1
WQ Max Comp Step=1HOUR
WQ Output Interval=15MIN
WQ Output Selected Increments= 0
WQ Create Restart=0
WQ Fixed Restart=0
WQ System Summary=0
WQ Write To DSS=0
Sorting and Armoring Iterations= 10
XS Update Threshold= 0.02
Bed Roughness Predictor= 0
Processes Affected by Predictor=Sediment Only
Hydraulics Update Threshold= 0.02
Energy Slope Method= 1
Volume Change Method= 1
Sediment Retention Method= 0
Sediment TS Multiplier= 1
Warm Up Method= 0
XS Weighting Method= 0
Number of US Weighted Cross Sections= 1
Number of DS Weighted Cross Sections= 1
Upstream XS Weight=0
Main XS Weight=1
Downstream XS Weight=0
Number of DS XS's Weighted with US Boundary= 1
Upstream Boundary Weight= 1
Weight of XSs Associated with US Boundary= 0
Number of US XS's Weighted with DS Boundary= 1
Downstream Boundary Weight= 0.5
Weight of XSs Associated with DS Boundary= 0.5
Percentile Method= 0
Sediment Output Level= 3
Mass or Volume Output= 0
Output Increment Type= 1
Profile and TS Output Increment= 1
Transport Output Increment 1
XS Output Flag= 0
XS Output Increment= 10
Read HDF5 Sediment Hotstart= 0
Sediment Hotstart Type= 0
Write Gradation File= 0
Read Gradation Hotstart= 0
Write HDF5 File= 1
Write Binary Output= 1
Write DSS Sediment File= 0
DSS Sediment Output Type= 1
SV Curve= 0
Specific Gage Flag= 0
Subcell Erosion Methods= 0
Subcell Deposition Methods= 0
Advection Scheme= 1
Matrix Solver= 0
Implicit Weighting Factor= 1
Maximum Outer Loop Convergence Iterations= 5
Convergence Maximum Absolute= 0.001
Convergence RMSE= 0.0001
Grain Fractions Max Abs Error= 0.001
Max Subgrid Regions= 1
Max Subgrid Length Scale= 3.402823E+38
Initial Layer Thickness= 3
Min Layer Thickness= 0.1
Max Layer Thickness= 6
Number of Layers= 5

--- HrtRnT1.f01 (steady flow) ---

Flow Title=Flow
Program Version=6.60
Number of Profiles= 1
Profile Names=P100yr
River Rch & RM=HrtRnT1,Main            ,639
    1070
Boundary for River Rch & Prof#=HrtRnT1,Main            , 1
Up Type= 0
Dn Type= 3
Dn Slope=0.027
DSS Import GetInterval= 0
DSS Import GetPeak= 0
DSS Import FillOption= 0

--- HrtRnT1.g01 (geometry) ---

Geom Title=Geometry
Program Version=6.60

River Reach=HrtRnT1         ,Main
Reach XY= 21
1682085.50527996467979.8681713071682066.99384312467980.567599404
1682037.96743443467979.3581657081682010.95674856467974.520430926
1681984.79994014467965.4400230651681946.63991147467958.960049137
1681891.91987656467945.279958397 1681851.6000753467946.000101313
1681826.39999448467956.7999484841681783.92009255467966.159837887
1681755.84009622467971.199854061 1681721.9999408467976.960013136
1681695.35990222467979.8399286421681655.04010098467983.439987063
1681624.80000398467983.4399870631681590.95984855467982.719844148
1681561.43989447467979.1201138051681541.28015789467977.680156067
1681491.60013914467976.9600131361681468.56015897467970.480039224
1681430.17703363467965.157543316

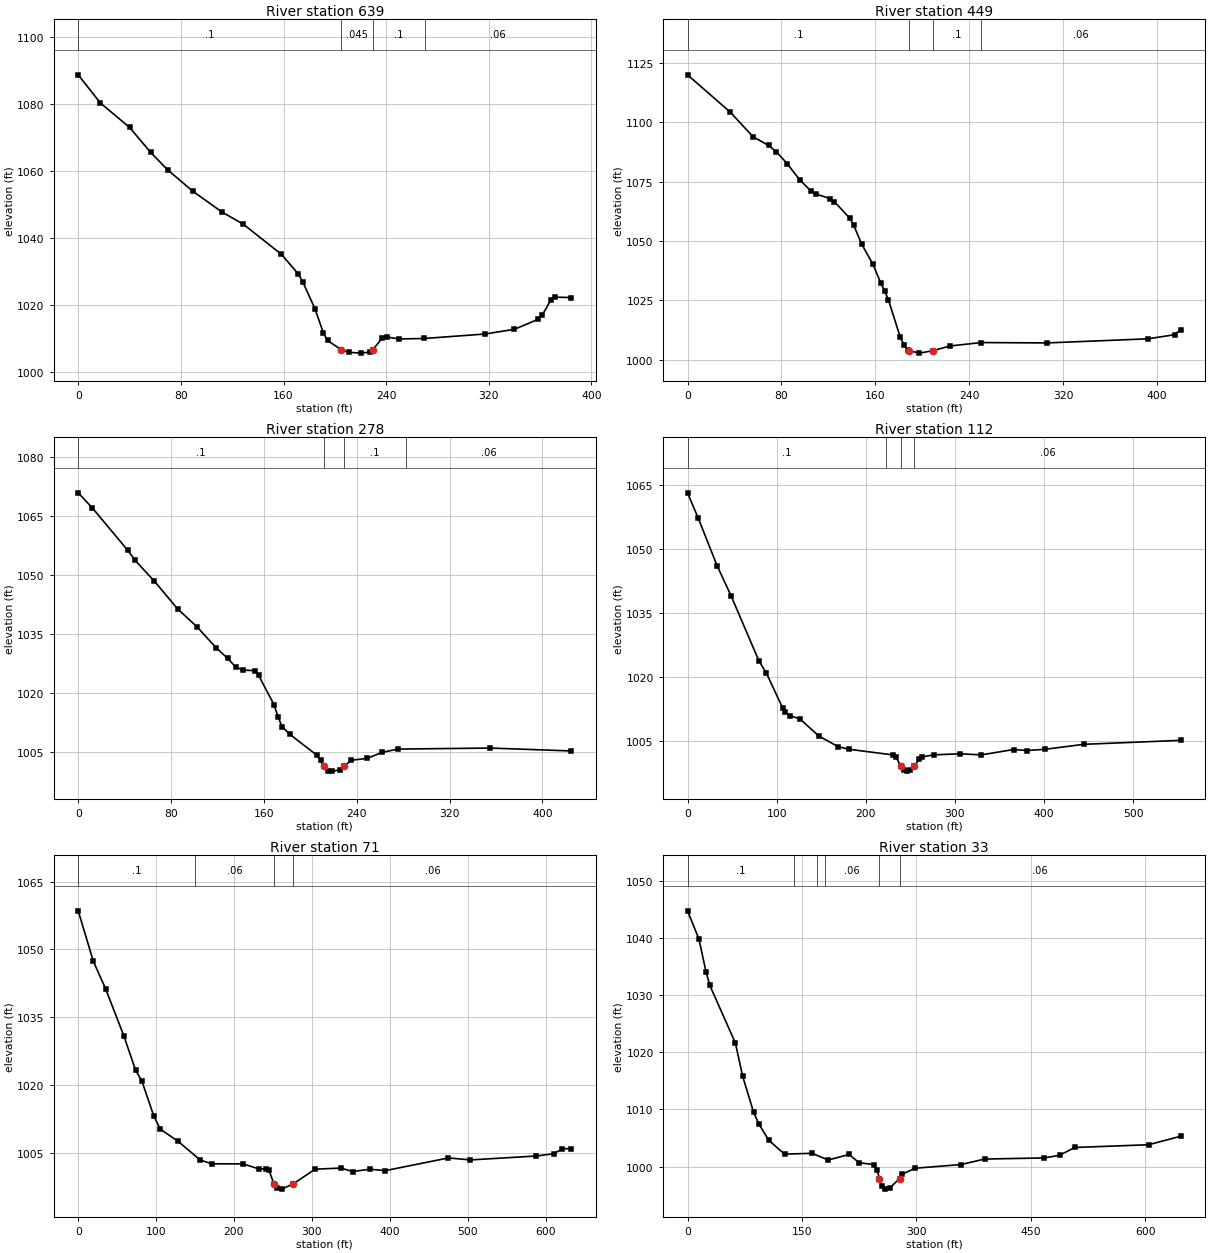
Type RM Length L Ch R = 1 ,639     ,189,189.8,187.6
XS GIS Cut Line= 2
1682060.86442059467765.7222466771682056.76515934468150.136202199
#Sta/Elev= 30
       0 1088.61    17.2 1080.26    40.1 1072.93    56.5  1065.5    69.6 1060.36
    89.3 1053.96   112.3  1047.7   128.7 1044.13   158.2 1035.22   171.4  1029.4
   174.9 1027.06   184.5 1018.98     191 1011.86   194.3 1009.52  204.871006.803
   210.7 1006.01   220.6 1005.76   227.1  1006.1  229.731006.804     237  1010.3
   240.3 1010.57   250.1 1009.98   269.8 1010.12   317.3 1011.46     340 1012.86
   358.4 1015.83   361.7 1017.11   368.2 1021.47   371.5 1022.42   384.4 1022.31
#Mann= 4 ,-1,0
       0      .1       0  204.87    .045       0  229.73      .1       0
     270     .06       0
Bank Sta=204.87,229.73
XS Rating Curve= 0 ,0
Exp/Cntr(USF)=0,0
Exp/Cntr=0.3,0.1

Type RM Length L Ch R = 1 ,449     ,170.9,171,169.3
XS GIS Cut Line= 2
 1681854.9308942467753.4265942151681894.24194312468171.973644498
#Sta/Elev= 30
       0  1119.9    36.2 1104.31    55.9 1093.85    69.1 1090.18    75.7 1087.57
    85.1 1082.44    95.5  1075.8   105.4 1070.94   109.2 1069.83   121.8 1067.78
   125.1 1066.58   138.3 1059.61   141.6 1056.68   148.3 1048.83   158.1 1040.14
   164.7 1032.35     168 1029.04   171.3 1025.16   181.2 1009.69   184.5 1006.23
   187.7 1004.25  189.191003.817   197.6 1002.82     2091003.815   223.6 1005.82
   250.4 1007.27   306.4 1007.11   392.1 1008.83   415.1 1010.55   420.4 1012.74
#Mann= 4 ,-1,0
       0      .1       0  189.19    .045       0     209      .1       0
     250     .06       0
Bank Sta=189.19,209
XS Rating Curve= 0 ,0
Exp/Cntr(USF)=0,0
Exp/Cntr=0.3,0.1

Type RM Length L Ch R = 1 ,278     ,164.6,165.9,167
XS GIS Cut Line= 6
1681670.54775667 467760.557146431681683.83906868467847.053036422
1681696.42401726467920.989896432 1681713.2044955468019.571720258
1681725.78977218468093.5082521741681740.47248558468179.767594084
#Sta/Elev= 30
       0 1070.89    12.3 1067.01    42.5 1056.33    49.1 1053.69    65.7 1048.39
    85.6 1041.37   102.3 1036.81   118.9 1031.45   128.9 1028.74   135.6 1026.59
   142.2 1025.78   152.2 1025.65   155.5 1024.42   168.8 1016.93   172.2 1013.92
   175.5 1011.43   182.2 1009.47   205.4 1004.18   208.8 1002.85  211.411001.371
   215.4  1000.2   218.8 1000.08   225.4 1000.37   229.2 1001.37   235.4 1002.86
   248.7  1003.3     262 1004.85   275.3 1005.69   355.2 1005.95     425 1005.21
#Mann= 4 ,-1,0
       0      .1       0  211.41    .045       0   229.2      .1       0
  282.51     .06       0
Bank Sta=211.41,229.2
XS Rating Curve= 0 ,0
Exp/Cntr(USF)=0,0
Exp/Cntr=0.3,0.1

Type RM Length L Ch R = 1 ,112     ,42,40.5,39.9
XS GIS Cut Line= 4
1681647.31281692467761.2675598341681538.83478676467931.949775111
1681544.14490013468053.3237948631681729.99886787468188.352391838
#Sta/Elev= 30
       0 1063.21      12 1057.27    33.3 1046.04    48.9 1039.01      80 1023.78
    88.4  1020.9   106.7 1012.68   109.4 1011.82     115 1010.84   126.1  1010.1
   147.4 1006.04   169.4 1003.53   181.1 1002.95   230.3 1001.63   233.6 1001.22
  239.69998.9044   243.5  997.96   246.8  997.81   250.1  997.97  254.39998.9035
   259.9 1000.59   263.2 1001.15   276.3 1001.64   305.9 1001.88   329.7 1001.63
     366 1002.89   380.5 1002.65   400.8 1002.93   444.8 1004.11   553.5 1005.04
#Mann= 4 ,-1,0
       0      .1       0  222.24     .06       0  239.69    .045       0
  254.39     .06       0
Bank Sta=239.69,254.39
XS Rating Curve= 0 ,0
Exp/Cntr(USF)=0,0
Exp/Cntr=0.3,0.1

Type RM Length L Ch R = 1 ,71      ,39,38.6,37.1
XS GIS Cut Line= 4
1681613.17637386467746.8543949881681495.59529222467928.915424617
1681509.24986945468066.9783720851681734.55039361468229.316123504
#Sta/Elev= 30
       0 1058.54    19.4  1047.4    35.1 1041.35    58.5 1030.97    73.6 1023.38
    81.9 1020.86      97 1013.24   105.4 1010.32   128.2 1007.64   156.7  1003.5
   171.8 1002.67   211.9 1002.65   231.5 1001.56   241.4 1001.55   244.9 1001.26
   251.2998.2571   254.6  997.34   261.2  997.08  276.25998.2579     304 1001.48
     337 1001.73   352.6 1000.97   374.3 1001.47   394.4 1001.17   475.3 1003.97
   503.6 1003.53   588.2  1004.4   610.3 1004.89   621.5 1005.98   633.2 1006.05
#Mann= 4 ,-1,0
       0      .1       0     150     .06       0   251.2    .045       0
  276.25     .06       0
Bank Sta=251.2,276.25
XS Rating Curve= 0 ,0
Exp/Cntr(USF)=0,0
Exp/Cntr=0.3,0.1

Type RM Length L Ch R = 1 ,33      ,,,
XS GIS Cut Line= 5
1681560.43334162467735.8738945911681453.12568555467911.335018914
1681468.31361241468004.0461680721681489.25721892468095.500619785
1681698.10294736468238.789393104
#Sta/Elev= 30
       0 1044.82      15 1039.87    24.3 1034.11    29.3 1031.74    62.8 1021.64
    72.3 1015.83    86.6 1009.53    93.5 1007.46   106.7 1004.59   127.2 1002.17
   163.3 1002.32   184.5 1001.14   211.8 1002.11   225.1 1000.66     245 1000.34
   248.4  999.45   251.7  997.88     255  996.53   258.3  996.04     265  996.22
  277.95  997.88   281.6  998.66   298.2   999.7   358.8 1000.35   389.4 1001.31
   467.9 1001.51   487.8 1001.97   507.7 1003.34   604.5 1003.82   646.7 1005.31
#Mann= 6 ,-1,0
       0      .1       0     140     .06       0     170      .1       0
     180     .06       0   251.7    .045       0  277.95     .06       0
Bank Sta=251.7,277.95
XS Rating Curve= 0 ,0
Exp/Cntr(USF)=0,0
Exp/Cntr=0.3,0.1
LCMann Table=0

Chan Stop Cuts=-1
Use User Specified Reach Order=0
Composite Channel Slope=5